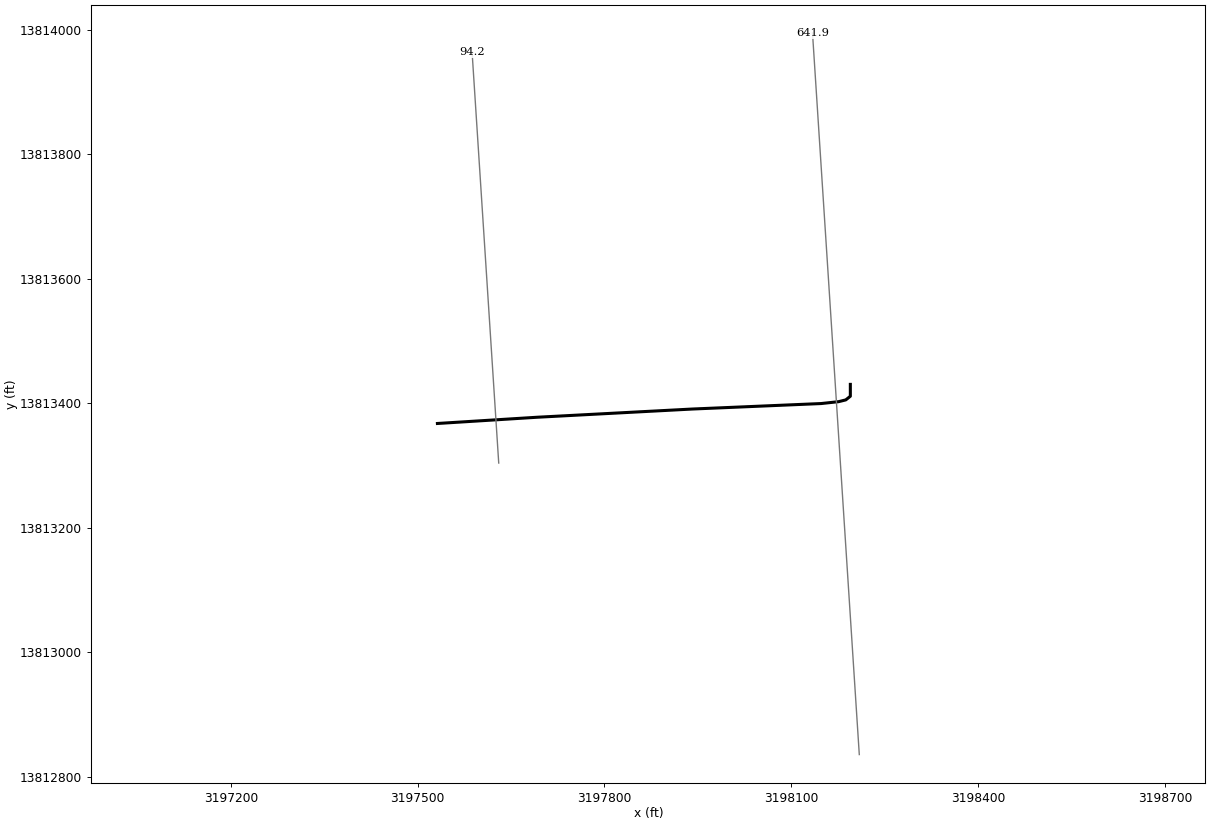
--- B114-02-00.prj (project) ---

Proj Title=B114-02-00
Current Plan=p09
Default Exp/Contr=.3,.1
English Units
Geom File=g03
Flow File=f04
Flow File=f01
Plan File=p09
Plan File=p01
Y Axis Title=Elevation
X Axis Title(PF)=Main Channel Distance
X Axis Title(XS)=Station
BEGIN DESCRIPTION:
Watershed: Armand Bayou
Stream name:
HCFCD Unit B114-02-00
(Flood Hazard, Floodway) Model
10. 2 1 0.2% Event
Filename: B114-02-00.prj
Prepared by: Ty Turner 2-2003, Revised by Sean Sutton 6-10-2003
Reviewed by:
STATUS: Final RAS
END DESCRIPTION:
DSS Export Rating Curves= 0
DSS Export Rating Curve Sorted= 0
DSS Export Volume Flow Curves= 0
DXF OffsetX= 0
DXF OffsetY= 0
DXF ScaleX= 1
DXF ScaleY= 10

--- B114-02-00.p09 (plan) ---

Plan Title=FEMA Effective June 2007
Version=Version 3.0.1  Mar 2001
Short Identifier=FEMAeff0607
Geom File=g03
Flow File=f04
Subcritical Flow
K Sum by GR= 0
Std Step Tol= 0.01
Critical Tol= 0.01
Num of Std Step Trials= 20
Max Error Tol= 0.3
Flow Tol Ratio= 0.001
Split Flow NTrial= 30
Split Flow Tol= 0.02
Split Flow Ratio= 0.02
Log Output Level= 0
Friction Slope Method= 0
Unsteady Friction Slope Method= 2
Secant Critical Depth
Global Vel Dist= 0 , 0 , 0
Global Log Level= 0
CheckData=True
Encroach Param=-1 ,0,0, 0
BEGIN DESCRIPTION:
Flood Hazard Run
END DESCRIPTION:
Computation Interval=1HOUR
Output Interval=1HOUR
Run HTab= 0
Run UNet= 0
Run PostProcess= 0
UNET Theta= 1
UNET ZTol= 0.02
UNET ZSATol= 0.1
UNET MxIter= 20
UNET MaxInSteps= 20
UNET DtIC= 0
UNET DtMin= 0
UNET MaxCRTS= 20
UNET WFStab= 2
UNET SFStab= 1
UNET WFX= 1
UNET SFX= 1
UNET Convert EG Bridges=-1
UNET Use Existing IB Tables=-1
Instantaneous Interval=1HOUR
DSS File=dss
Write IC File= 0
IC Time=0
Write Velocity= 0
Write Detailed= 0

--- B114-02-00.p01 (plan) ---

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Plan Title=Floodway
Short Identifier=Floodway0607
Geom File=g03
Flow File=f01
Encroach Param=-1 ,0,0, 2
Encroach River=B114-02-00
Encroach Reach=2
Encroach Node=641.9
       1  553.19  581.95
Encroach Node=94.2
       1   55.13   83.89
Encroach Reach=B114-02-00_0001
Encroach Node=641.9
       1  553.19  581.95
Encroach Node=94.2
       1   55.13   83.89
Floodway Run

--- B114-02-00.f04 (steady flow) ---

Flow Title=FEMA Effective June 2007
Version=Version 3.0.1  Mar 2001
Number of Profiles= 4
Profile Names=10PCT_10yr, 2PCT_50yr, 1PCT_100yr, 0.2PCT_500yr
River Rch & RM=B114-02-00,B114-02-00_0001               ,641.9
      18      26      30      42
River Rch & RM=B114-02-00,B114-02-00_0001               ,94.2
      29      42      49      69
Boundary for River Rch & Prof#=B114-02-00,B114-02-00_0001               , 1
Up Type= 0
Dn Type= 3
Dn Slope=.002
Boundary for River Rch & Prof#=B114-02-00,B114-02-00_0001               , 2
Up Type= 0
Dn Type= 3
Dn Slope=.002
DSS Import GetInterval= 0
DSS Import GetPeak= 0
DSS Import FillOption= 0

--- B114-02-00.f01 (steady flow) ---

Flow Title=Floodway
Version=Version 3.0.1  Mar 2001
Number of Profiles= 2
Profile Names=1PCT_100yr, 1PCTFloodway_100yrFW
River Rch & RM=B114-02-00,B114-02-00_0001               ,641.9
      30      30
River Rch & RM=B114-02-00,B114-02-00_0001               ,94.2
      49      49
Boundary for River Rch & Prof#=B114-02-00,B114-02-00_0001               , 1
Up Type= 0
Dn Type= 3
Dn Slope=.002
Boundary for River Rch & Prof#=B114-02-00,B114-02-00_0001               , 2
Up Type= 0
Dn Type= 3
Dn Slope=.002
DSS Import GetInterval= 0
DSS Import GetPeak= 0
DSS Import FillOption= 0

--- B114-02-00.g03 (geometry) ---

Geom Title=B114-02-00 June 2007
Version=Version 3.0.1  Mar 2001

River Reach=B114-02-00      ,B114-02-00_0001
Reach XY= 30
     3198194.907    13813430.484     3198194.907    13813411.415
     3198187.746    13813405.686     3198187.572    13813405.548
     3198176.126    13813402.713     3198147.967     13813399.68
     3198139.164    13813399.306     3198121.645     13813398.56
     3198048.005    13813395.427     3198031.645     13813394.73
     3198010.754    13813393.842     3197986.645    13813392.816
     3197976.066    13813392.365     3197941.142    13813390.879
      3197887.92    13813388.062     3197881.645    13813387.729
     3197876.001    13813387.431     3197856.243    13813386.385
      3197847.51    13813385.922     3197824.566    13813384.708
     3197746.645    13813380.582     3197731.645    13813379.788
     3197729.535    13813379.677     3197705.051     13813378.38
     3197691.777    13813377.678     3197656.645    13813375.479
     3197596.645    13813371.725     3197591.997    13813371.435
     3197566.645    13813369.848     3197531.689    13813367.661

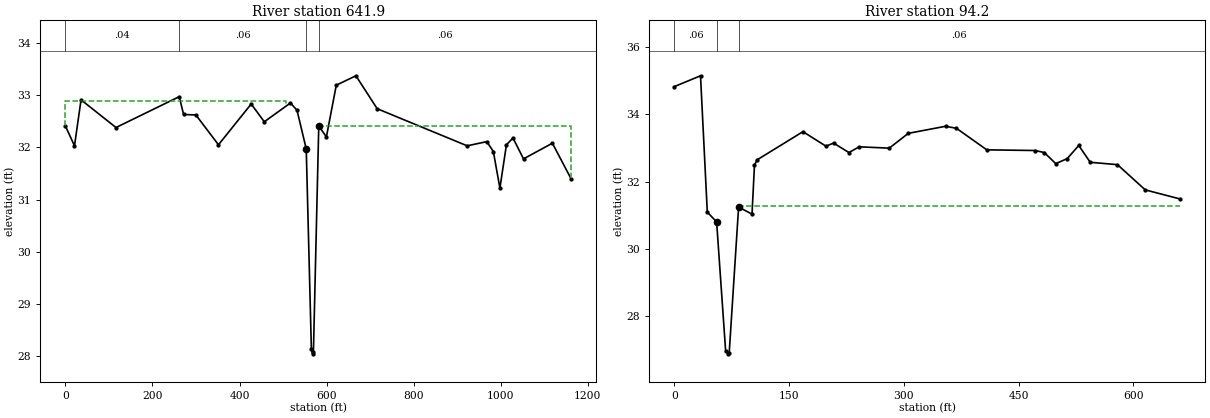
Type RM Length L Ch R = 1 ,641.9   ,547.69,547.7,548.56
BEGIN DESCRIPTION:
B114-02-00-v2 - survey data used for stations 541.01-599.49
END DESCRIPTION:
XS GIS Cut Line= 4
     3198209.283    13812835.909     3198176.928    13813334.861
     3198166.484    13813495.915     3198134.129    13813994.867
#Sta/Elev= 30
       0   32.41   20.92   32.03   35.95   32.91  116.24   32.38  261.43   32.97
  271.52   32.63  299.75   32.62  351.61   32.05  426.75   32.83  456.84   32.49
  516.96   32.85  531.99   32.71  553.19   31.97  564.98   28.14   567.8   28.05
  569.66   28.08  581.95   32.41  599.49    32.2  622.18   33.19  667.28   33.37
  716.08   32.74  922.81   32.03  967.91   32.11  982.94   31.92  997.97   31.22
    1013   32.05 1028.03   32.18 1052.18   31.78 1118.48   32.08 1161.39    31.4
#Mann= 4 ,-1 , 0
       0     .04       0  261.43     .06       0  553.19     .04       0
  581.95     .06       0
#XS Ineff= 2 , 0
       0  507.12   32.88   584.9       0   32.41
Permanent Ineff=
       F       F
Bank Sta=553.19,581.95
XS Rating Curve= 0
Exp/Cntr=.3,.1

Type RM Length L Ch R = 1 ,94.2    ,0,0,0
BEGIN DESCRIPTION:
Channel area survey points copied from cross-section 641.9 (stations 42.95 - 101.43).  Elevation of survey points adjusted such that the channel invert point matches the channel invert of the downstream-most cross-section for stream B114-01-00 (XS 29, channel area from survey).
END DESCRIPTION:
XS GIS Cut Line= 3
     3197630.167    13813304.112     3197619.723    13813465.165
     3197587.368    13813964.117
#Sta/Elev= 30
       0   34.83   34.06   35.15   42.95    31.1   55.13   30.81   66.92   26.98
   69.74   26.89    71.6   26.92   83.89   31.25  101.43   31.04  104.64   32.49
   107.9   32.65  168.03   33.49  198.09   33.06  208.14   33.15  228.15   32.87
  241.74   33.04  280.93      33  305.86   33.44  354.57   33.65  368.79   33.59
  408.53   32.95  471.66   32.93  483.69   32.87  498.72   32.54  513.75   32.69
  528.78   33.08  543.81   32.58   579.4   32.51   615.8   31.76  661.39   31.49
#Mann= 3 , 0 , 0
       0     .06       0   55.13     .04       0   83.89     .06       0
#XS Ineff= 2 , 0
       0                    84.9       0   31.29
Permanent Ineff=
       F       F
Bank Sta=55.13,83.89
XS Rating Curve= 0
Exp/Cntr=.3,.1

Chan Stop Cuts=-1